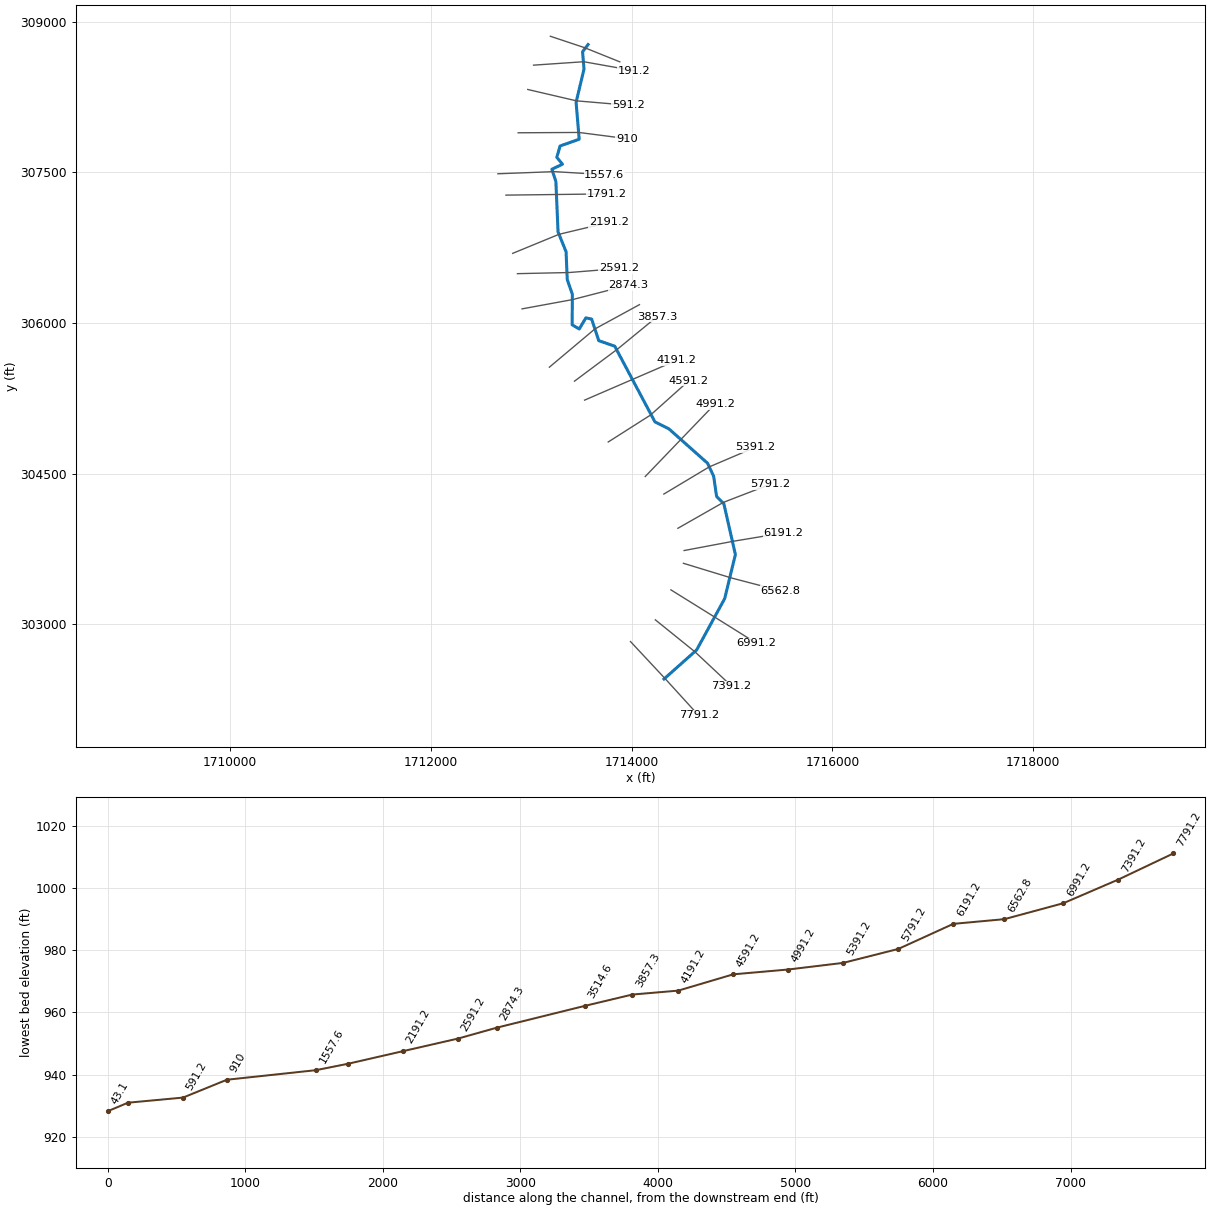
--- GregryRn.prj (project) ---

Proj Title=GregryRn
Current Plan=p01
Default Exp/Contr=0,0
English Units
Geom File=g01
Flow File=f01
Plan File=p01
BEGIN DESCRIPTION:
END DESCRIPTION:
DSS Export Rating Curves= 0
DSS Export Rating Curve Sorted= 0
DSS Export Volume Flow Curves= 0
DXF OffsetX= 0
DXF OffsetY= 0
DXF ScaleX= 0
DXF ScaleY= 0

--- GregryRn.p01 (plan) ---

Plan Title=Floodplain
Program Version=4.00
Geom File=g01
Flow File=f01
K Sum by GR=0
Std Step Tol=0.01
Critical Tol=0.01
Num of Std Step Trials=20
Max Error Tol=0.3
Flow Tol Ratio=0.001
Split Flow NTrial=30
Split Flow Tol=0.02
Split Flow Ratio=0.02
Log Output Level=0
Friction Slope Method=1
Unsteady Friction Slope Method=2
Unsteady Bridges Friction Slope Method=1
Global Log Level=0
CheckData=False
Run HTab=0
Run UNet=0
Run PostProcess=0
UNET Theta=0
UNET Theta Warmup=0
UNET ZTol=0
UNET ZSATol=0
UNET MxIter=0
UNET MaxInSteps=0
UNET DtIC=0
UNET DtMin=0
UNET MaxCRTS=0
UNET WFStab=0
UNET SFStab=0
UNET WFX=0
UNET SFX=0
UNET DSS MLevel=0
UNET DZMax Abort=0
UNET Convert EG Bridges=0
UNET Use Existing IB Tables=0
UNET Froude Limit=0
UNET Froude Power=0
Write IC File=0
Echo Input=False
Echo Output=False
Write Detailed=0

--- GregryRn.f01 (steady flow) ---

Flow Title=NFF Regression Equation
Program Version=4.00
Number of Profiles= 1
Profile Names=P100yr
River Rch & RM=GregryRn,Main            ,7791.2
     722
River Rch & RM=GregryRn,Main            ,6991.2
743.2307
River Rch & RM=GregryRn,Main            ,6562.8
824.3312
River Rch & RM=GregryRn,Main            ,6191.2
828.2421
River Rch & RM=GregryRn,Main            ,5791.2
 918.619
River Rch & RM=GregryRn,Main            ,3857.3
996.4169
River Rch & RM=GregryRn,Main            ,2591.2
1076.806
River Rch & RM=GregryRn,Main            ,191.2
  1159.5
River Rch & RM=GregryRn,Main            ,43.1
  1162.6
Boundary for River Rch & Prof#=GregryRn,Main            , 1
Up Type= 0
Dn Type= 3
Dn Slope=0.012
DSS Import GetInterval= 0
DSS Import GetPeak= 0
DSS Import FillOption= 0

--- GregryRn.g01 (geometry) ---

Geom Title=USGS 3m DEM
Program Version=4.00

River Reach=GregryRn     ,Main
Reach XY= 30
     1714323.173      302456.666     1714647.047      302744.808
     1714926.890      303256.697     1715033.501      303695.614
     1714918.645      304201.265     1714846.730      304273.684
     1714816.512      304477.004     1714755.905      304605.366
     1714371.267      304947.469     1714232.347      305016.776
     1713832.061      305770.449     1713672.885      305825.252
     1713602.682      306039.805     1713544.738      306052.252
     1713478.646      305941.522     1713408.105      305983.198
     1713410.275      306286.997     1713359.107      306433.765
     1713347.591      306710.735     1713267.718      306908.116
     1713246.058      307408.873     1713206.501      307532.327
     1713311.894      307582.302     1713255.196      307651.518
     1713288.205      307763.878     1713478.112      307831.103
     1713447.337      308198.885     1713526.181      308529.932
     1713511.711      308702.171     1713566.368      308773.515

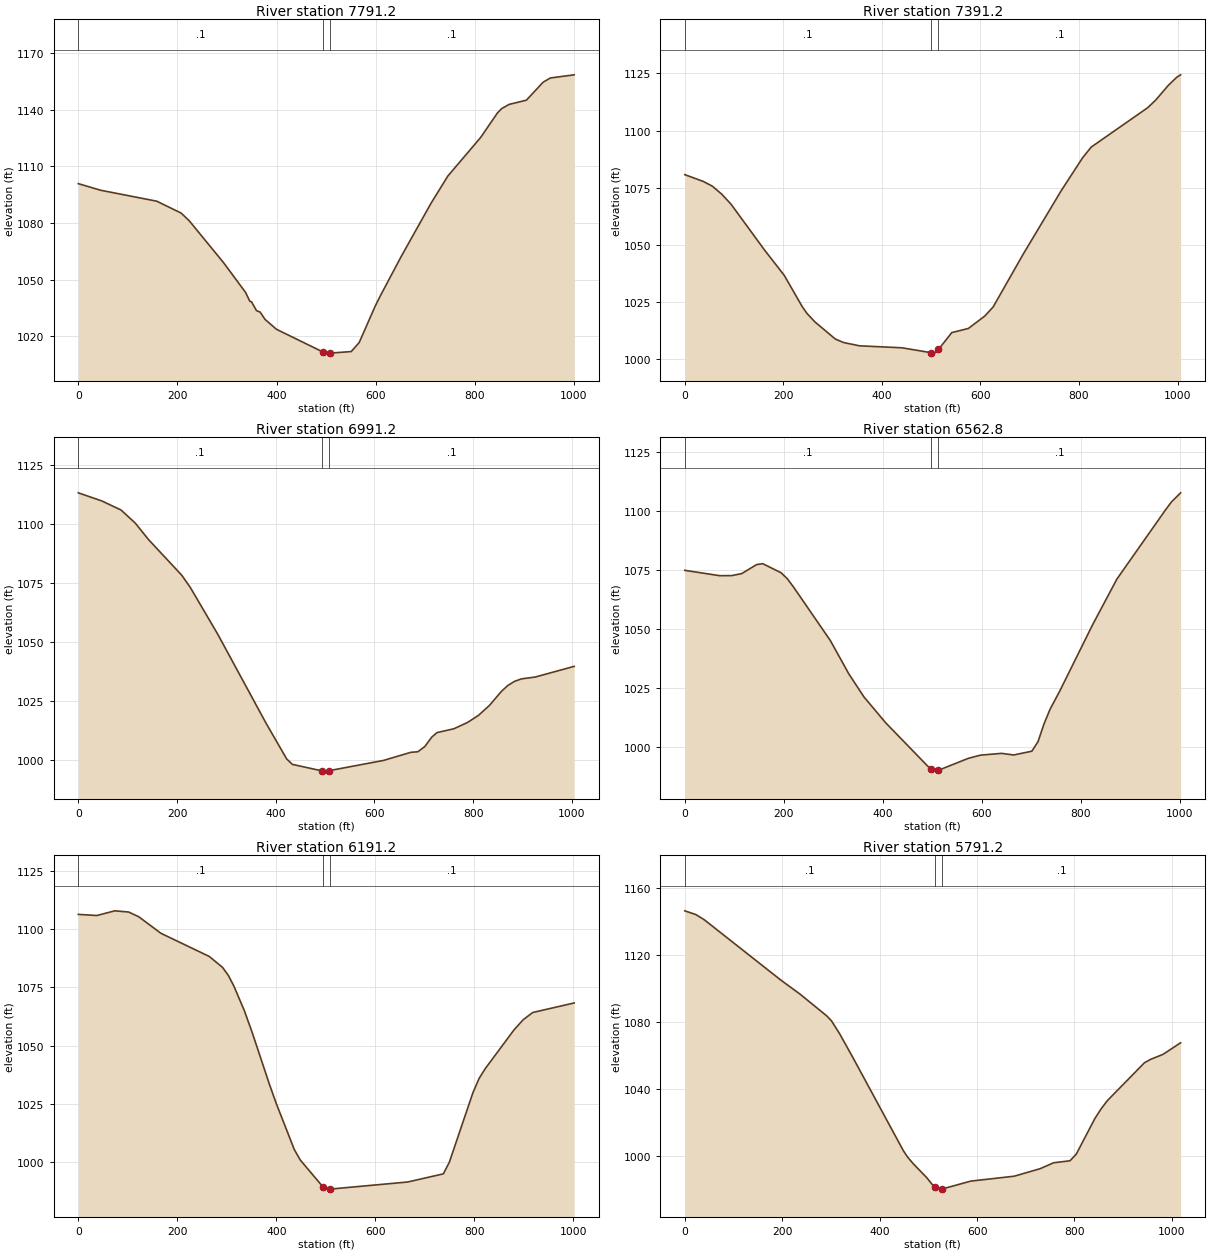
Type RM Length L Ch R = 1 ,7791.2,396.836,400,401.783
XS GIS Cut Line= 3
     1713988.974      302829.270     1714330.566      302463.400
     1714667.581      302093.382
#Sta/Elev= 30
       0 1100.83    45.0 1097.33   158.1 1091.54   207.4 1085.24   223.7 1081.18
   292.8 1059.03   337.4 1043.21   346.0 1038.53   349.4 1038.26   359.4 1033.56
   366.8 1032.80   376.8 1028.89   399.8 1023.67     493 1011.72     508 1011.05
   550.6 1011.89   566.7 1016.68   598.8 1035.90   609.8 1041.66   651.9 1062.48
   711.2 1090.28   745.4 1104.83   811.6 1125.27   845.2 1138.16   853.6 1140.50
   868.9 1142.79   903.9 1145.04   937.6 1154.53   952.1 1156.79  1000.3 1158.47
#Mann= 3 , 0 , 0
       0     0.1       0     493   0.045       0     508     0.1       0
Bank Sta=     493,     508
Exp/Cntr=0.3,0.1

Type RM Length L Ch R = 1 ,7391.2,397.182,400,404.415
XS GIS Cut Line= 3
     1714236.531      303045.309     1714631.276      302726.618
     1714995.481      302385.503
#Sta/Elev= 30
       0 1080.72    37.2 1077.78    56.1 1075.66    75.0 1072.18    93.9 1067.79
   162.1 1047.68   201.9 1036.67   238.1 1023.09   247.7 1020.10   264.0 1016.34
   305.6 1008.82   322.5 1007.29   354.5 1005.87   440.7 1005.00   499.8 1002.87
   507.1 1002.67   514.8 1004.27   541.9 1011.65   575.5 1013.46   609.1 1018.93
   625.9 1022.90   686.0 1045.65   763.6 1073.58   807.6 1088.17   824.9 1092.78
   939.4 1109.98   955.7 1113.32   981.3 1119.75   998.6 1123.35  1006.3 1124.37
#Mann= 3 , 0 , 0
       0     0.1       0   499.8   0.045       0   514.8     0.1       0
Bank Sta=   499.8,   514.8
Exp/Cntr=0.3,0.1

Type RM Length L Ch R = 1 ,6991.2,422.419,428.426,435.326
XS GIS Cut Line= 3
     1714391.329      303343.974     1714816.579      303079.537
     1715243.887      302812.240
#Sta/Elev= 30
       0 1113.15    47.7 1109.70    86.6 1105.85   115.2 1100.35   142.6 1093.24
   209.6 1078.18   226.9 1073.01   282.4 1053.21   380.2 1015.49   422.2 1000.25
   433.8  997.93   493.3  995.20   502.7  995.07   508.3  995.27   618.1  999.59
   674.1 1003.06   688.1 1003.29   702.1 1005.49   716.1 1009.46   726.7 1011.41
   761.2 1013.05   788.4 1015.68   810.8 1018.71   833.2 1022.96   857.1 1028.84
   870.2 1031.39   884.2 1033.18   898.2 1034.21   926.2 1035.01  1004.8 1039.52
#Mann= 3 , 0 , 0
       0     0.1       0   493.3   0.045       0   508.3     0.1       0
Bank Sta=   493.3,   508.3
Exp/Cntr=0.3,0.1

Type RM Length L Ch R = 1 ,6562.8,360.789,371.574,381.038
XS GIS Cut Line= 3
     1714515.987      303608.371     1714995.908      303461.739
     1715479.939      303335.322
#Sta/Elev= 30
       0 1074.86    70.7 1072.59    94.8 1072.63   114.9 1073.46   145.2 1077.29
   157.6 1077.67   194.9 1073.80   207.3 1071.28   219.1 1067.99   294.2 1045.16
   331.4 1031.11   362.2 1021.30   405.9 1010.42   496.7  990.82   504.9  989.95
   511.7  990.24   573.0  995.36   597.7  996.71   640.2  997.46   664.7  996.78
   701.5  998.38   713.8 1002.39   726.1 1009.97   738.3 1016.14   757.9 1023.84
   824.2 1051.84   873.3 1071.16   971.9 1100.52   983.8 1103.84  1002.1 1107.63
#Mann= 3 , 0 , 0
       0     0.1       0   496.7   0.045       0   511.7     0.1       0
Bank Sta=   496.7,   511.7
Exp/Cntr=0.3,0.1

Type RM Length L Ch R = 1 ,6191.2,392.491,400,404.598
XS GIS Cut Line= 3
     1714523.023      303735.547     1715015.776      303828.398
     1715509.064      303910.293
#Sta/Elev= 30
       0 1106.22    37.5 1105.74    73.7 1107.75   101.7 1107.23   122.1 1105.20
   166.8 1098.12   264.3 1088.21   291.2 1083.53   303.3 1079.96   314.0 1075.58
   335.5 1064.87   351.6 1055.33   386.3 1033.21   399.9 1025.09   436.2 1005.44
   448.3 1000.93   493.9  989.46   496.6  988.78   508.4  988.44   508.9  988.46
   665.1  991.49   737.3  994.99   749.4  999.98   796.9 1029.69   809.5 1035.90
   821.6 1040.00   880.0 1056.71   898.6 1061.07   917.9 1064.17  1001.5 1068.25
#Mann= 3 , 0 , 0
       0     0.1       0   493.9   0.045       0   508.9     0.1       0
Bank Sta=   493.9,   508.9
Exp/Cntr=0.3,0.1

Type RM Length L Ch R = 1 ,5791.2,399.736,400,400.581
XS GIS Cut Line= 3
     1714460.988      303957.043     1714913.721      304214.995
     1715377.194      304393.963
#Sta/Elev= 30
       0 1146.15    22.4 1143.96    39.8 1140.88   197.6 1104.80   236.8 1096.50
   291.5 1083.54   300.9 1080.72   317.6 1073.07   344.5 1059.09   448.9 1003.18
   457.6  999.42   469.1  995.48   496.4  987.32   510.1  982.40   513.6  981.68
   523.6  980.39   528.6  980.49   587.2  985.17   676.3  988.09   729.6  992.57
   757.1  996.09   790.8  997.27   803.6 1001.20   841.7 1022.35   854.5 1028.13
   867.6 1033.13   943.6 1055.65   956.3 1057.68   981.7 1060.65  1017.9 1067.57
#Mann= 3 , 0 , 0
       0     0.1       0   513.6   0.045       0   528.6     0.1       0
Bank Sta=   513.6,   528.6
Exp/Cntr=0.3,0.1

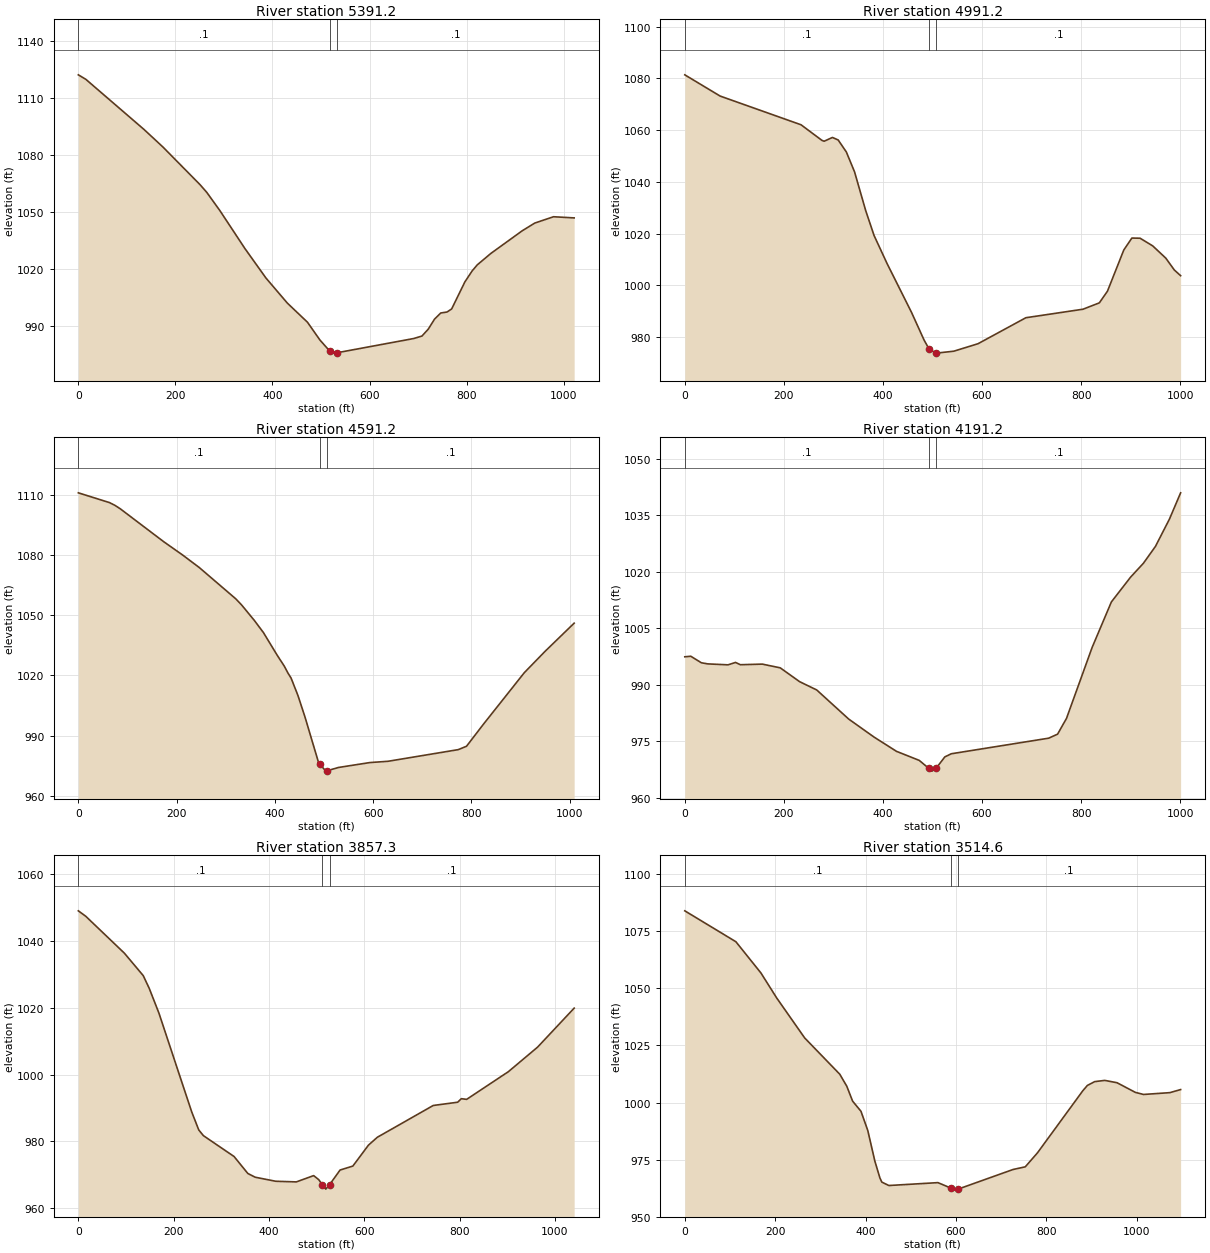
Type RM Length L Ch R = 1 ,5391.2,394.006,400,409.078
XS GIS Cut Line= 3
     1714320.978      304297.799     1714771.931      304567.808
     1715228.200      304762.496
#Sta/Elev= 30
       0 1122.29    15.5 1119.92   135.6 1093.50   174.3 1084.33   250.8 1064.52
   264.6 1060.49   291.4 1050.99   343.3 1030.92   386.6 1015.43   430.7 1002.23
   472.2  992.17   497.8  982.83   518.1  976.98   527.4  975.92   533.1  976.12
   690.9  983.59   708.1  984.91   721.0  988.51   733.9  993.77   746.8  997.02
   759.8  997.55   769.3  999.17   796.5 1013.37   811.4 1019.12   822.0 1022.33
   850.1 1028.36   914.7 1040.27   940.5 1044.32   979.2 1047.65  1021.7 1047.04
#Mann= 3 , 0 , 0
       0     0.1       0   518.1   0.045       0   533.1     0.1       0
Bank Sta=   518.1,   533.1
Exp/Cntr=0.3,0.1

Type RM Length L Ch R = 1 ,4991.2,405.482,400,398.247
XS GIS Cut Line= 3
     1714136.006      304472.774     1714482.952      304833.507
     1714829.899      305194.241
#Sta/Elev= 30
       0 1081.42    71.4 1073.20   234.7 1062.10   276.8 1056.08   281.3 1055.74
   298.1 1057.20   309.7 1056.22   326.2 1051.56   342.7 1043.90   365.3 1028.86
   382.1 1019.29   408.6 1008.34   457.7  989.56   482.8  978.96     493  975.41
   507.4  973.79     508  973.80   543.0  974.53   592.0  977.43   688.6  987.48
   803.9  990.77   836.9  993.23   853.3  997.74   886.3 1013.69   902.6 1018.29
   919.2 1018.23   944.7 1015.26   971.1 1010.52   988.3 1005.94  1001.0 1003.74
#Mann= 3 , 0 , 0
       0     0.1       0     493   0.045       0     508     0.1       0
Bank Sta=     493,     508
Exp/Cntr=0.3,0.1

Type RM Length L Ch R = 1 ,4591.2,403.577,400,392.694
XS GIS Cut Line= 3
     1713767.277      304816.382     1714188.037      305084.198
     1714567.968      305424.631
#Sta/Elev= 30
       0 1111.16    63.3 1106.29    74.1 1104.96    85.4 1103.18   173.8 1086.75
   211.7 1080.21   246.1 1073.87   320.3 1058.26   332.1 1055.23   357.9 1047.54
   376.6 1041.41   404.7 1030.07   418.8 1024.77   426.7 1021.14   432.9 1018.71
   447.0 1009.91   461.3  999.18   489.2  976.21   491.3  975.66   503.8  972.24
   506.3  972.42   529.2  974.06   593.1  976.51   630.1  977.15   773.1  982.97
   789.9  984.66   824.4  995.69   907.6 1021.42   950.2 1032.15  1008.9 1046.10
#Mann= 3 , 0 , 0
       0     0.1       0   491.3   0.045       0   506.3     0.1       0
Bank Sta=   491.3,   506.3
Exp/Cntr=0.3,0.1

Type RM Length L Ch R = 1 ,4191.2,328.579,333.865,339.264
XS GIS Cut Line= 3
     1713531.880      305233.238     1713991.306      305431.803
     1714450.732      305630.368
#Sta/Elev= 30
       0  997.39    12.1  997.53    33.4  995.80    46.4  995.50    87.3  995.25
   102.4  995.89   112.2  995.28   156.6  995.44   192.7  994.45   231.9  990.77
   266.3  988.58   330.9  980.84   382.7  976.00   427.5  972.26   473.2  969.87
     493  967.71   499.1  967.01     508  967.87   524.9  970.78   537.9  971.62
   734.5  975.76   752.6  976.83   770.6  981.02   822.4  999.89   861.2 1011.96
   900.0 1018.55   925.9 1022.24   950.2 1026.72   978.4 1033.96  1001.0 1040.95
#Mann= 3 , 0 , 0
       0     0.1       0     493   0.045       0     508     0.1       0
Bank Sta=     493,     508
Exp/Cntr=0.3,0.1

Type RM Length L Ch R = 1 ,3857.3,340.169,342.763,340.552
XS GIS Cut Line= 3
     1713431.255      305421.827     1713864.222      305744.794
     1714251.232      306062.049
#Sta/Elev= 30
       0 1048.92    15.7 1047.28    96.6 1036.27   136.3 1029.54   149.0 1025.68
   169.1 1018.37   237.9  988.84   252.7  983.45   262.4  981.74   326.8  975.50
   355.7  970.43   371.2  969.31   414.3  968.10   457.5  967.91   493.8  969.79
   504.5  968.58   512.2  967.02   519.3  965.75   527.2  967.07   549.3  971.46
   576.1  972.64   608.8  978.89   627.5  981.25   744.8  990.75   796.0  991.72
   803.8  992.78   814.8  992.57   902.4 1000.84   963.8 1008.19  1040.5 1019.84
#Mann= 3 , 0 , 0
       0     0.1       0   512.2   0.045       0   527.2     0.1       0
Bank Sta=   512.2,   527.2
Exp/Cntr=0.3,0.1

Type RM Length L Ch R = 1 ,3514.6,652.096,640.318,634.408
XS GIS Cut Line= 3
     1713181.365      305561.243     1713633.942      305941.623
     1714078.012      306183.874
#Sta/Elev= 30
       0 1083.85   113.0 1070.34   168.4 1056.69   203.3 1045.75   265.3 1028.25
   342.9 1012.39   358.4 1007.14   371.3 1000.62   389.8  996.18   404.9  987.76
   420.4  974.47   431.7  967.01   435.9  965.22   451.4  963.72   560.0  964.98
   588.7  962.60   603.7  962.15   604.6  962.14   726.3  970.73   753.3  971.89
   780.4  978.04   880.6 1005.16   890.8 1007.50   906.9 1009.15   929.2 1009.69
   956.2 1008.68   996.8 1004.46  1014.8 1003.54  1073.1 1004.33  1097.0 1005.68
#Mann= 3 , 0 , 0
       0     0.1       0   588.7   0.045       0   603.7     0.1       0
Bank Sta=   588.7,   603.7
Exp/Cntr=0.3,0.1

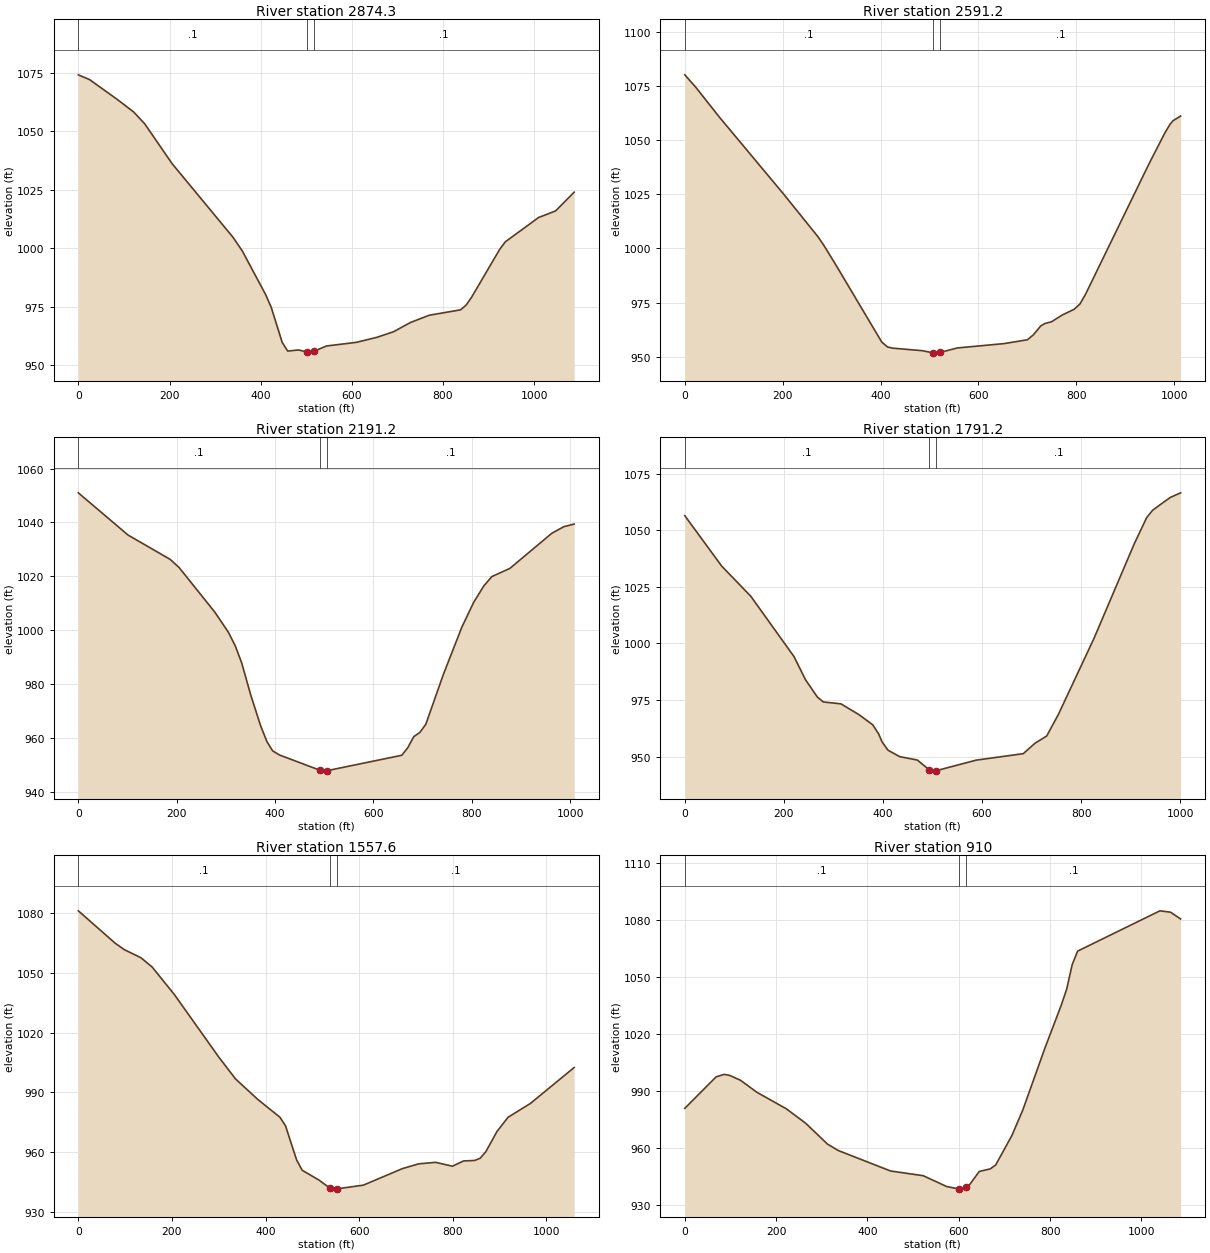
Type RM Length L Ch R = 1 ,2874.3,286.477,283.054,279.331
XS GIS Cut Line= 3
     1712909.048      306141.804     1713411.549      306234.132
     1713970.609      306378.380
#Sta/Elev= 30
       0 1074.22    24.7 1072.17    85.0 1063.75   121.3 1058.33   145.4 1053.32
   205.8 1036.19   339.3 1004.71   359.7  998.85   411.0  980.13   423.0  974.80
   447.2  959.73   459.3  956.02   483.4  956.50   501.2  955.62   507.5  955.14
   516.2  955.87   544.3  958.19   610.0  959.76   654.6  961.88   691.4  964.29
   728.2  968.22   769.8  971.36   838.5  973.66   850.8  975.73   863.1  979.21
   924.4  999.58   936.6 1002.77  1009.6 1013.17  1047.0 1016.00  1087.6 1024.01
#Mann= 3 , 0 , 0
       0     0.1       0   501.2   0.045       0   516.2     0.1       0
Bank Sta=   501.2,   516.2
Exp/Cntr=0.3,0.1

Type RM Length L Ch R = 1 ,2591.2,391.963,400,403.339
XS GIS Cut Line= 3
     1712863.219      306492.446     1713377.505      306503.694
     1713874.735      306543.907
#Sta/Elev= 30
       0 1080.18    22.6 1074.40    70.1 1060.80   200.8 1025.41   272.0 1005.44
   283.9 1001.52   309.1  992.24   402.6  956.72   414.5  954.45   425.3  953.92
   485.8  952.75   506.9  951.77   509.5  951.63   521.9  951.96   557.1  954.02
   652.4  956.03   700.1  957.79   712.0  960.00   727.4  964.18   735.8  965.30
   749.5  966.12   771.5  969.25   795.4  971.84   807.3  974.23   819.2  978.92
   947.8 1038.66   980.9 1053.28   991.9 1057.41   997.9 1059.01  1013.3 1061.13
#Mann= 3 , 0 , 0
       0     0.1       0   506.9   0.045       0   521.9     0.1       0
Bank Sta=   506.9,   521.9
Exp/Cntr=0.3,0.1

Type RM Length L Ch R = 1 ,2191.2,408.534,400,395.003
XS GIS Cut Line= 3
     1712816.046      306694.681     1713277.471      306884.394
     1713773.097      307002.692
#Sta/Elev= 30
       0 1051.00   101.1 1035.31   186.8 1026.27   205.0 1023.23   277.8 1006.61
   305.1  999.22   319.4  994.02   332.2  987.81   350.5  975.94   370.7  964.46
   383.5  958.55   395.2  955.11   409.2  953.58   491.4  947.91   498.9  947.59
   506.4  947.78   657.7  953.48   670.0  956.30   682.2  960.42   694.4  961.95
   706.6  964.98   742.2  983.45   779.8 1001.04   804.2 1010.38   824.9 1016.48
   840.8 1019.87   877.5 1022.91   962.9 1035.97   987.3 1038.42  1008.3 1039.39
#Mann= 3 , 0 , 0
       0     0.1       0   491.4   0.045       0   506.4     0.1       0
Bank Sta=   491.4,   506.4
Exp/Cntr=0.3,0.1

Type RM Length L Ch R = 1 ,1791.2,233.409,233.635,233.042
XS GIS Cut Line= 3
     1712748.768      307274.530     1713249.231      307280.611
     1713749.694      307286.693
#Sta/Elev= 30
       0 1056.51    74.6 1034.18   133.3 1020.86   220.2  994.29   243.9  983.88
   267.7  976.30   279.6  974.13   315.2  973.29   350.8  968.64   379.6  964.00
   391.4  959.97   398.3  956.46   410.2  952.80   433.9  949.94   469.5  948.44
     493  944.22   505.2  943.54     508  943.76   588.3  948.40   683.3  951.26
   707.0  955.87   730.7  959.09   754.5  968.74   826.1 1002.24   907.5 1044.13
   932.6 1055.71   944.5 1058.90   958.3 1061.14   980.1 1064.57  1001.0 1066.61
#Mann= 3 , 0 , 0
       0     0.1       0     493   0.045       0     508     0.1       0
Bank Sta=     493,     508
Exp/Cntr=0.3,0.1

Type RM Length L Ch R = 1 ,1557.6,597.775,647.591,645.62
XS GIS Cut Line= 3
     1712669.026      307487.017     1713230.476      307508.448
     1713727.326      307478.408
#Sta/Elev= 30
       0 1081.17    78.3 1065.01    98.2 1061.69   133.8 1057.63   157.6 1053.00
   205.1 1039.19   300.1 1007.78   335.8  996.83   383.3  986.54   430.8  977.57
   442.7  973.29   466.5  956.13   478.4  950.95   514.0  946.07   537.8  941.97
   549.6  941.48   552.8  941.61   609.1  943.48   692.4  951.76   727.5  954.18
   763.7  954.93   799.4  952.98   823.2  955.62   847.0  955.87   858.9  957.01
   870.8  960.25   894.6  970.38   918.3  977.53   965.9  984.45  1059.6 1002.52
#Mann= 3 , 0 , 0
       0     0.1       0   537.8   0.045       0   552.8     0.1       0
Bank Sta=   537.8,   552.8
Exp/Cntr=0.3,0.1

Type RM Length L Ch R = 1 ,910,323.549,318.774,319.677
XS GIS Cut Line= 3
     1712870.575      307895.270     1713474.357      307898.518
     1713952.519      307837.046
#Sta/Elev= 30
       0  980.89    68.7  997.46    86.5  998.74    98.4  998.20   122.1  995.63
   157.7  989.36   222.3  980.65   264.6  973.08   312.1  962.17   335.8  958.74
   450.6  947.95   522.2  945.47   573.3  939.79   600.8  938.46   608.9  938.41
   615.8  939.27   620.9  939.80   644.9  947.70   668.8  949.04   680.8  951.07
   716.7  966.75   740.6  980.23   788.5 1012.43   824.4 1035.09   836.4 1043.57
   848.3 1056.34   860.3 1063.54  1040.5 1084.73  1063.8 1084.02  1085.9 1080.44
#Mann= 3 , 0 , 0
       0     0.1       0   600.8   0.045       0   615.8     0.1       0
Bank Sta=   600.8,   615.8
Exp/Cntr=0.3,0.1

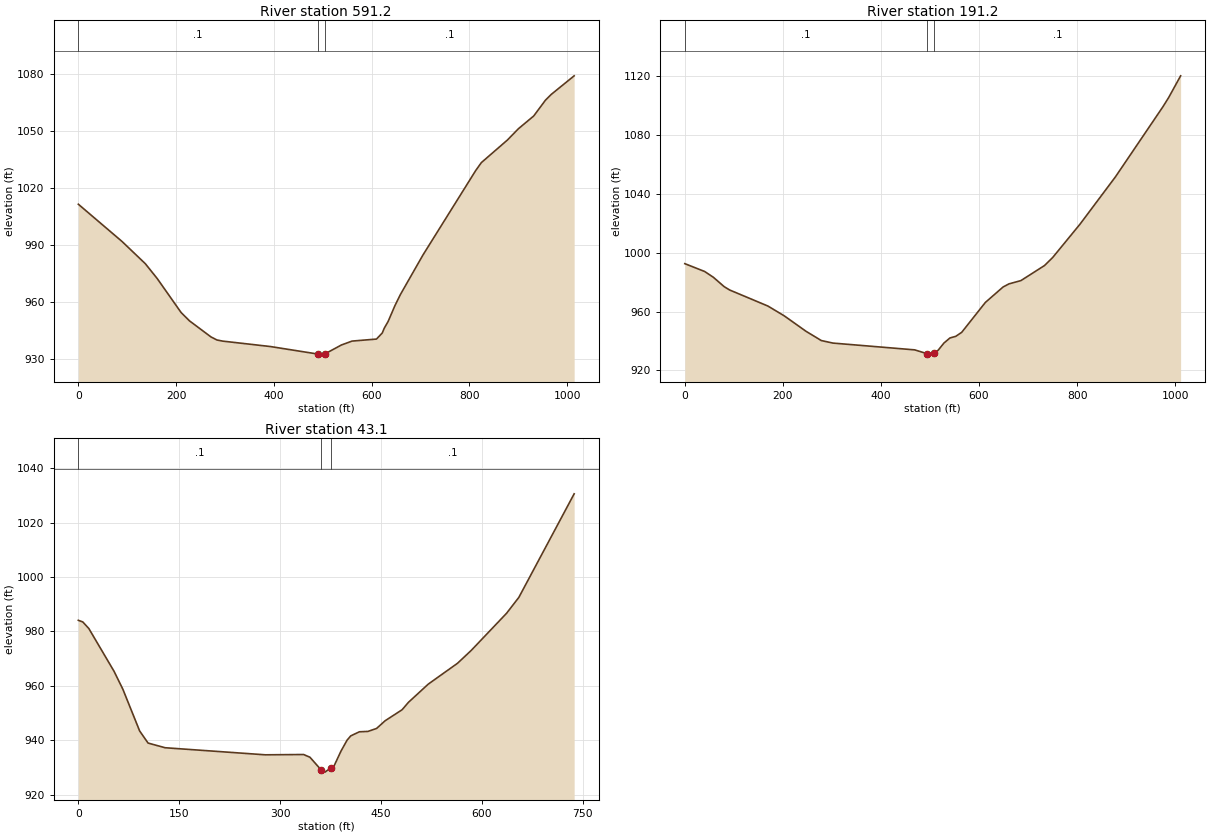
Type RM Length L Ch R = 1 ,591.2,393.298,400,397.565
XS GIS Cut Line= 3
     1712966.073      308326.398     1713450.704      308213.314
     1713965.494      308169.469
#Sta/Elev= 30
       0 1011.45    89.2  991.92   137.1  980.18   161.4  972.39   210.2  954.56
   227.5  950.14   271.2  941.75   283.4  940.12   295.5  939.51   393.1  936.66
   490.1  932.71   490.6  932.68   505.1  932.90   538.4  937.51   560.0  939.53
   609.9  940.59   621.8  943.80   625.8  946.29   633.8  949.87   647.8  958.24
   658.8  963.97   705.2  984.85   812.8 1029.10   824.4 1033.30   877.6 1045.14
   900.4 1051.14   931.6 1057.82   955.5 1066.09   967.4 1069.14  1014.3 1078.91
#Mann= 3 , 0 , 0
       0     0.1       0   490.1   0.045       0   505.1     0.1       0
Bank Sta=   490.1,   505.1
Exp/Cntr=0.3,0.1

Type RM Length L Ch R = 1 ,191.2,157.122,148.124,143.735
XS GIS Cut Line= 3
     1713023.660      308568.619     1713523.790      308602.736
     1714025.775      308513.402
#Sta/Elev= 30
       0  992.59    40.4  987.27    58.1  983.37    80.3  976.94    91.5  974.67
   169.5  963.75   202.9  957.07   247.4  946.53   278.4  940.28   302.2  938.55
   468.8  933.94   493.8  931.38   504.4  931.04   508.8  931.96   516.6  933.65
   528.6  938.61   540.7  942.02   552.7  943.16   564.8  945.89   613.0  966.21
   649.2  976.73   661.3  978.85   685.4  981.05   733.6  991.30   750.3  996.78
   806.0 1019.45   878.3 1051.66   974.8 1099.18   986.9 1105.64  1011.2 1120.37
#Mann= 3 , 0 , 0
       0     0.1       0   493.8   0.045       0   508.8     0.1       0
Bank Sta=   493.8,   508.8
Exp/Cntr=0.3,0.1

Type RM Length L Ch R = 1 ,43.1,50.652,43.091,36.788
XS GIS Cut Line= 3
     1713191.120      308856.366     1713532.889      308742.255
     1713882.651      308601.592
#Sta/Elev= 30
       0  984.08     6.6  983.48    15.6  981.07    53.1  965.35    66.2  958.77
    91.2  943.42   103.7  938.98   129.1  937.26   278.0  934.66   335.0  934.77
   344.4  933.77   360.6  929.24   366.7  928.30   375.6  929.88   379.5  930.16
   390.5  935.99   399.6  940.03   405.1  941.62   417.9  943.12   430.7  943.26
   443.5  944.35   456.3  947.19   481.4  951.21   490.9  953.94   520.3  960.62
   563.9  968.30   584.3  973.03   636.9  986.69   655.1  992.52   737.3 1030.55
#Mann= 3 , 0 , 0
       0     0.1       0   360.6   0.045       0   375.6     0.1       0
Bank Sta=   360.6,   375.6
Exp/Cntr=0.3,0.1